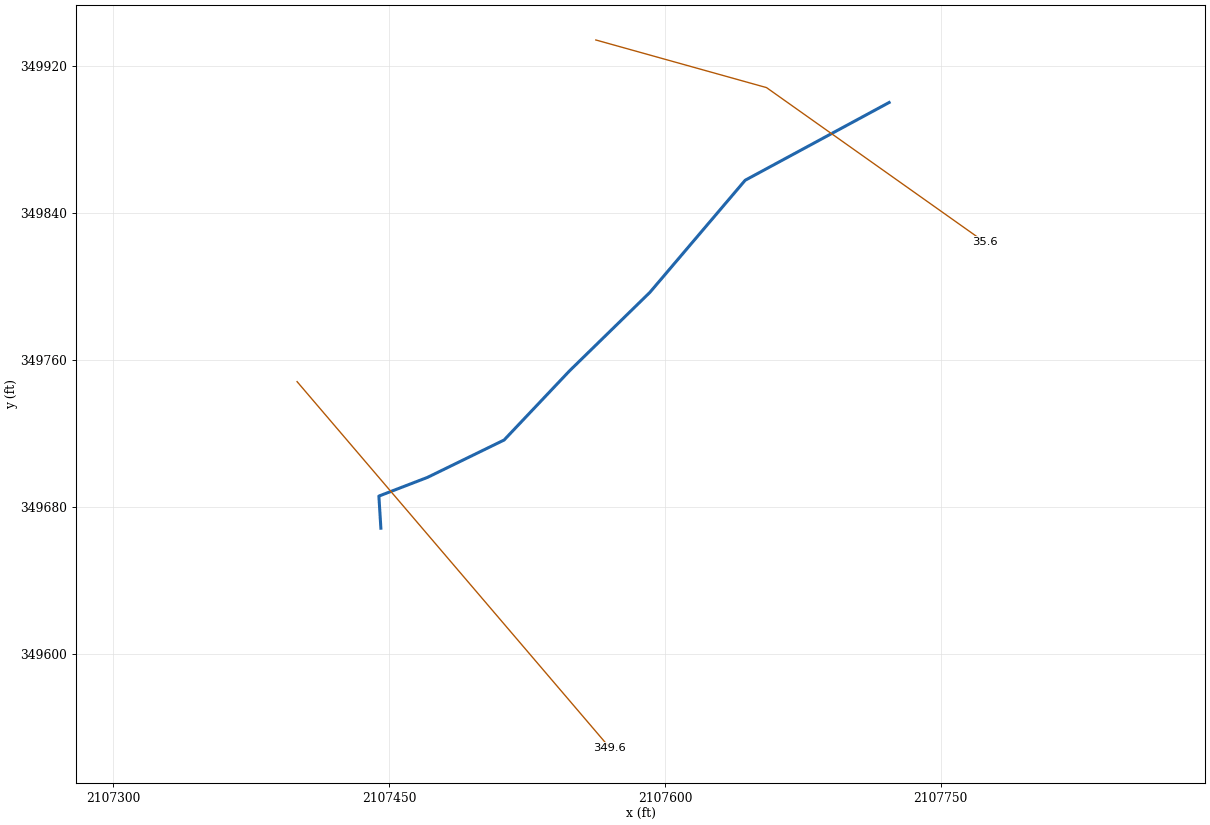
--- NP139.prj (project) ---

Proj Title=NP139
Current Plan=p01
Default Exp/Contr=0,0
English Units
Geom File=g01
Flow File=f01
Plan File=p01
BEGIN DESCRIPTION:
END DESCRIPTION:
DSS Export Rating Curves= 0
DSS Export Rating Curve Sorted= 0
DSS Export Volume Flow Curves= 0
DXF OffsetX= 0
DXF OffsetY= 0
DXF ScaleX= 0
DXF ScaleY= 0

--- NP139.p01 (plan) ---

Plan Title=Floodplain
Program Version=4.00
Geom File=g01
Flow File=f01
K Sum by GR=0
Std Step Tol=0.01
Critical Tol=0.01
Num of Std Step Trials=20
Max Error Tol=0.3
Flow Tol Ratio=0.001
Split Flow NTrial=30
Split Flow Tol=0.02
Split Flow Ratio=0.02
Log Output Level=0
Friction Slope Method=1
Unsteady Friction Slope Method=2
Unsteady Bridges Friction Slope Method=1
Global Log Level=0
CheckData=False
Run HTab=0
Run UNet=0
Run PostProcess=0
UNET Theta=0
UNET Theta Warmup=0
UNET ZTol=0
UNET ZSATol=0
UNET MxIter=0
UNET MaxInSteps=0
UNET DtIC=0
UNET DtMin=0
UNET MaxCRTS=0
UNET WFStab=0
UNET SFStab=0
UNET WFX=0
UNET SFX=0
UNET DSS MLevel=0
UNET DZMax Abort=0
UNET Convert EG Bridges=0
UNET Use Existing IB Tables=0
UNET Froude Limit=0
UNET Froude Power=0
Write IC File=0
Echo Input=False
Echo Output=False
Write Detailed=0

--- NP139.f01 (steady flow) ---

Flow Title=NFF Regression Equation
Program Version=4.00
Number of Profiles=1
Profile Names=P100yr
River Rch & RM=NP139,Main      ,349.6
      29
River Rch & RM=NP139,Main      ,35.6
      29
Boundary for River Rch & Prof#=NP139,Main      ,1
Up Type=0
Dn Type=3
Dn Slope=0.291976

--- NP139.g01 (geometry) ---

Geom Title=USGS 10m DEM
Program Version=4.00

River Reach=NP139           ,Main
Reach XY= 8
     2107445.472      349668.567     2107444.389      349686.021
     2107470.817      349696.186     2107512.493      349716.515
     2107548.069      349754.125     2107591.777      349796.816
     2107643.617      349857.804     2107721.906      349900.095

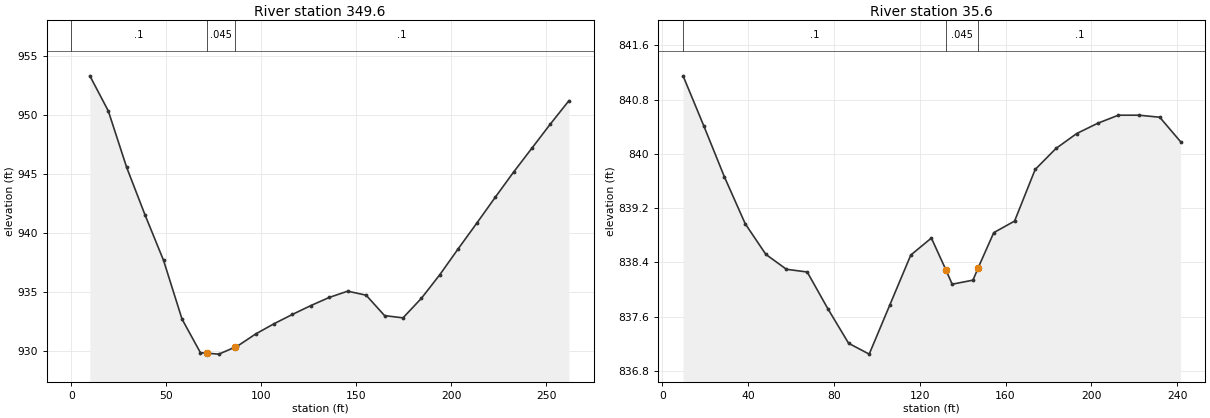
Type RM Length L Ch R = 1 ,349.6   ,307.9,314,320.9
XS GIS Cut Line= 2
     2107399.885      349748.281      2107569.88      349549.236
#Sta/Elev= 29
     9.7  953.33    19.4  950.36    29.1  945.57    38.8  941.53    48.5   937.7
    58.2  932.74    67.9  929.89    71.1  929.85    77.6  929.77    86.1  930.36
    87.3  930.44    96.9  931.47   106.6  932.34   116.3  933.13     126  933.88
   135.7  934.57   145.4   935.1   155.1  934.76   164.8  933.03   174.5  932.84
   184.2   934.5   193.9   936.5   203.6   938.7   213.3  940.85     223  943.04
   232.7  945.18   242.4  947.22   252.1  949.26   261.8  951.22
#Mann= 3 , 0 , 0
       0      .1       0    71.1    .045       0    86.1      .1       0
Bank Sta=71.1,86.1
XS Rating Curve= 0 ,0
Exp/Cntr=0.3,0.1

Type RM Length L Ch R = 1 ,35.6    ,46.8,35.6,24.5
XS GIS Cut Line= 3
     2107562.376      349934.107      2107655.22      349908.197
     2107773.725      349824.261
#Sta/Elev= 27
     9.6  841.15    19.3  840.41    28.9  839.66    38.6  838.97    48.2  838.52
    57.8   838.3    67.5  838.26    77.1  837.72    86.8  837.21    96.4  837.05
   106.1  837.78   115.8  838.51   125.4  838.76   132.2  838.29   135.1  838.08
   144.8  838.14   147.2  838.32   154.5  838.84   164.2  839.01   173.8  839.77
   183.5  840.08   193.2   840.3   202.9  840.45   212.6  840.57   222.2  840.57
   231.9  840.54   241.6  840.18
#Mann= 3 , 0 , 0
     9.6      .1       0   132.2    .045       0   147.2      .1       0
#XS Ineff= 2 , 0
          125.11  838.74
Permanent Ineff=
       F       F
Bank Sta=132.2,147.2
XS Rating Curve= 0 ,0
Exp/Cntr=0.3,0.1

Chan Stop Cuts=-1
Use User Specified Reach Order=0